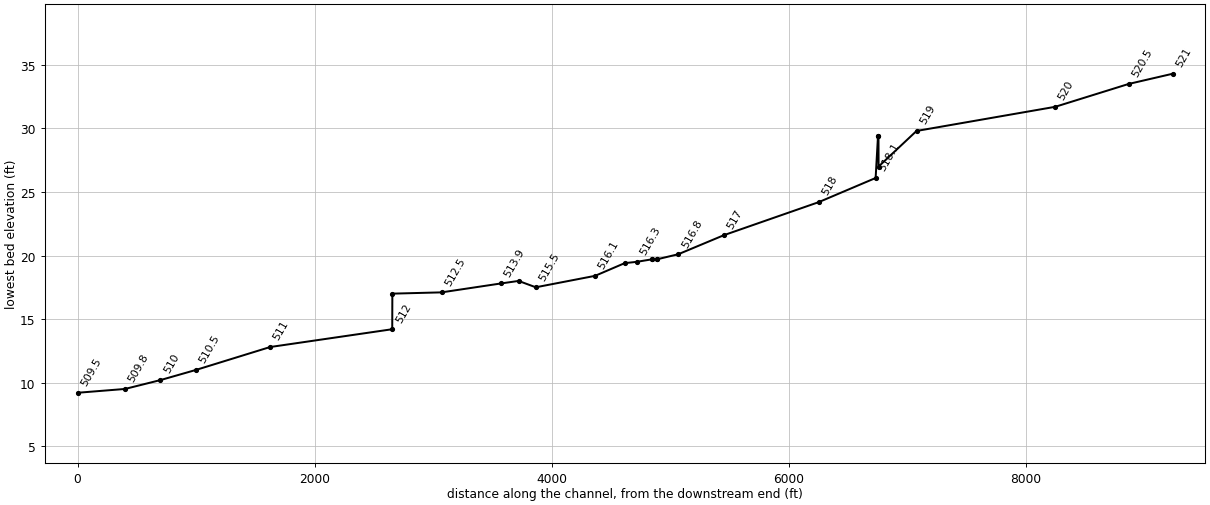
--- WMATA_JD.prj (project) ---

Proj Title=WMATA_JD
Current Plan=p03
Default Exp/Contr=0.3,0.1
English Units
Geom File=g01
Geom File=g02
Geom File=g03
Flow File=f01
Flow File=f02
Plan File=p01
Plan File=p02
Plan File=p03
Y Axis Title=Elevation
X Axis Title(PF)=Main Channel Distance
X Axis Title(XS)=Station
BEGIN DESCRIPTION:
      ANACOSTIA WATERSHED STUDY                      FILENAME:  NW2_WL.DAT
      PRINCE GEORGE'S COUNTY, MARYLAND               2- YR EXISTING CONDITIONS
      NORTHWEST BRANCH UPSTREAM OF TRIBUTARY 1 - WITH LEVEE
END DESCRIPTION:
DSS File=dss
DSS Export Rating Curves= 0
DSS Export Rating Curve Sorted= 0
DSS Export Volume Flow Curves= 0
DXF OffsetX= 0
DXF OffsetY= 0
DXF ScaleX= 1
DXF ScaleY= 10

--- WMATA_JD.p03 (plan) ---

Plan Title=Full Buildout
Program Version=4.10
Short Identifier=Full Buildout
Geom File=g03
Flow File=f02
Subcritical Flow
K Sum by GR= 0
Std Step Tol= 0.01
Critical Tol= 0.01
Num of Std Step Trials= 20
Max Error Tol= 0.3
Flow Tol Ratio= 0.001
Split Flow NTrial= 30
Split Flow Tol= 0.02
Split Flow Ratio= 0.02
Log Output Level= 0
Friction Slope Method= 1
Unsteady Friction Slope Method= 2
Unsteady Bridges Friction Slope Method= 1
Parabolic Critical Depth
Global Vel Dist= 0 , 0 , 0
Global Log Level= 0
CheckData=True
Encroach Param=-1 ,0,0, 6
Encroach River=RIVER-1
Encroach Reach=Reach-1
Encroach Node=500
       0       0       0       0       0       0       0       0       0
       0       0       0       0       0       0
Encroach Node=509.1
       0       0       0       0       0       0       0       0       0
       0       0       0       0       0       0
Encroach Node=509.2
       0       0       0       0       0       0       0       0       0
       0       0       0       0       0       0
Encroach Node=509.25
       0                       0                       0
       0                       0
Encroach Node=509.3
       0       0       0       0       0       0       0       0       0
       0       0       0       0       0       0
Encroach Node=509.4
       0       0       0       0       0       0       0       0       0
       0       0       0       0       0       0
Encroach Node=509.5
       0       0       0       0       0       0       0       0       0
       0       0       0       0       0       0
Encroach Node=509.8
       0       0       0       0       0       0       0       0       0
       0       0       0       0       0       0
Encroach Node=510
       1       1     455       1       1     455       1       1     455
       1       1     455       1       1     455
Encroach Node=510.5
       1    1000    1242       1    1000    1242       1    1000    1242
       1    1000    1242       1    1000    1242
Encroach Node=511
       1       1     400       1       1     400       1       1     400
       1       1     400       1       1     400
Encroach Node=512
       1     215     930       1     215     930       1     215     930
       1     215     930       1     215     930
Encroach Node=512.1
       1     240     930       1     240     930       1     240     930
       1     240     930       1     240     930
Encroach Node=512.5
       1       1     355       1       1     355       1       1     355
       1       1     355       1       1     355
Encroach Node=513.9
       0                       0                       0
       0                       0
Encroach Node=514.4
       0                       0                       0
       0                       0
Encroach Node=514.9
       0                       0                       0
       0                       0
Encroach Node=515.5
       0                       0                       0
       0                       0
Encroach Node=516.1
       0                       0                       0
       0                       0
Encroach Node=516.2
       0                       0                       0
       0                       0
Encroach Node=516.3
       0                       0                       0
       0                       0
Encroach Node=516.4
       0                       0                       0
       0                       0
Encroach Node=516.5
       0                       0                       0
       0                       0
Encroach Node=516.6
       0                       0                       0
       0                       0
Encroach Node=516.7
       0                       0                       0
       0                       0
Encroach Node=516.8
       0                       0                       0
       0                       0
Encroach Node=517
       0                       0                       0
       0                       0
Encroach Node=518
       0                       0                       0
       0                       0
Encroach Node=518.1
       0                       0                       0
       0                       0
Encroach Node=518.2
       0                       0                       0
       0                       0
Encroach Node=518.3
       0                       0                       0
       0                       0
Encroach Node=518.4
       0                       0                       0
       0                       0
Encroach Node=519
       0                       0                       0
       0                       0
Encroach Node=520
       0                       0                       0
       0                       0
Encroach Node=520.5
       0                       0                       0
       0                       0
Encroach Node=521
       0                       0                       0
       0                       0
Encroach Node=522
       0                       0                       0
       0                       0
Encroach Node=523
       0                       0                       0
       0                       0
Encroach Node=523.2
       0                       0                       0
       0                       0
Encroach Node=523.5
       0                       0                       0
       0                       0
Encroach Node=523.8
       0                       0                       0
       0                       0
Encroach Node=524
       0                       0                       0
       0                       0
Encroach Node=525
       0                       0                       0
       0                       0
Encroach Node=525.3
       0                       0                       0
       0                       0
Encroach Node=525.5
       0                       0                       0
       0                       0
Encroach Node=526
       0                       0                       0
       0                       0
Encroach Node=527
       0                       0                       0
       0                       0
Encroach Node=528
       0                       0                       0
       0                       0
Encroach Node=528.1
       0                       0                       0
       0                       0
Encroach Node=528.5
       0                       0                       0
       0                       0
Encroach Node=529
       0                       0                       0
       0                       0
Encroach Node=529.5
       0                       0                       0
       0                       0
Encroach Node=530
       0                       0                       0
       0                       0
Encroach Node=530.1
       0                       0                       0
       0                       0
Encroach Node=530.15
       0                       0                       0
       0                       0
Encroach Node=530.2
       0                       0                       0
       0                       0
Encroach Node=532
       0                       0                       0
       0                       0
Encroach Node=532.6
       0                       0                       0
       0                       0
Encroach Node=533.1
       0                       0                       0
       0                       0
Encroach Node=533.5
       0                       0                       0
       0                       0
Encroach Node=534
       0                       0                       0
       0                       0
Encroach Node=535
       0                       0                       0
       0                       0
Encroach Node=535.5
       0                       0                       0
       0                       0
Encroach Node=536.5
       0                       0                       0
       0                       0
Encroach Node=537
       0                       0                       0
       0                       0
Encroach Node=538
       0                       0                       0
       0                       0
Encroach Node=539
       0                       0                       0
       0                       0
Encroach Node=539.5
       0                       0                       0
       0                       0
Encroach Node=540
       0                       0                       0
       0                       0
Encroach Node=541
       0                       0                       0
       0                       0
Encroach Node=541.5
       0                       0                       0
       0                       0
Encroach Node=542
       0                       0                       0
       0                       0
Encroach Node=542.5
       0                       0                       0
       0                       0
Encroach Node=542.8
       0                       0                       0
       0                       0
Encroach Node=543
       0                       0                       0
       0                       0
Encroach Node=543.5
       0                       0                       0
       0                       0
Encroach Node=544
       0                       0                       0
       0                       0
Encroach Node=545.5
       0                       0                       0
       0                       0
Encroach Node=545.6
       0                       0                       0
       0                       0
Encroach Node=545.8
       0                       0                       0
       0                       0
Encroach Node=546
       0                       0                       0
       0                       0
Encroach Node=546.1
       0                       0                       0
       0                       0
Encroach Node=546.4
       0                       0                       0
       0                       0
Encroach Node=546.5
       0                       0                       0
       0                       0
Encroach Node=547
       0                       0                       0
       0                       0
Encroach Node=548
       0                       0                       0
       0                       0
Encroach Node=549
       0                       0                       0
       0                       0
Encroach Node=550
       0                       0                       0
       0                       0
Encroach Node=550.5
       0                       0                       0
       0                       0
Encroach Node=551
       0                       0                       0
       0                       0
Encroach Node=552
       0                       0                       0
       0                       0
Encroach Node=553
       0                       0                       0
       0                       0
Encroach Node=553.5
       0                       0                       0
       0                       0
Encroach Node=554
       0                       0                       0
       0                       0
Encroach Node=555.5
       0                       0                       0
       0                       0
Encroach Node=557
       0                       0                       0
       0                       0
Encroach Node=557.5
       0                       0                       0
       0                       0
Computation Interval=1HOUR
Output Interval=1HOUR
Run HTab= 0
Run UNet= 0
Run PostProcess= 0
Run WQNet= 0
UNET Theta= 1
UNET Theta Warmup= 1
UNET ZTol= 0.02
UNET ZSATol= 0.05
UNET MxIter= 20
UNET MaxInSteps= 0
UNET DtIC= 0
UNET DtMin= 0
UNET MaxCRTS= 20
UNET WFStab= 2
UNET SFStab= 1
UNET WFX= 1
UNET SFX= 1
UNET DSS MLevel= 4
UNET DZMax Abort= 100
UNET Convert EG Bridges= 0
UNET Use Existing IB Tables=-1
UNET Froude Reduction=False
UNET Froude Limit= 1
UNET Froude Power= 10
UNET Time Slicing=0,0, 5
UNET Junction Losses=0
Instantaneous Interval=1HOUR
DSS File=dss
Write IC File= 0
Write IC File at Sim End=0
Echo Input=False
Echo Parameters=False
Echo Output=False
Write Detailed= 0
WQ AD Non Conservative
WQ ULTIMATE=-1
WQ Max Comp Step=1HOUR
WQ Output Interval=15MIN
WQ Output Selected Increments= 0
WQ Output face flow=0
WQ Output face velocity=0
WQ Output face area=0
WQ Output face dispersion=0
WQ Output cell volume=0
WQ Output cell surface area=0
WQ Output cell continuity=0
WQ Output cumulative cell continuity=0
WQ Output face conc=0
WQ Output face dconc_dx=0
WQ Output face courant=0
WQ Output face peclet=0
WQ Output face adv mass=0
WQ Output face disp mass=0
WQ Output cell mass=0
WQ Output cell source sink temp=0
WQ Output cell source sink nsm=0
WQ Output MaxMinRange=-1
WQ Daily Max Min Mean=-1
WQ Daily Range=0
WQ Daily Time=0
WQ Create Restart=0
WQ Fixed Restart=0
WQ System Summary=0
WQ Use Fixed Temperature=0
Sorting and Armoring Iterations= 10
XS Update Threshold= 0.02
Hydraulics Update Threshold= 0.02
Energy Slope Method= 1
Volume Change Method= 0
XS Weighting Method= 0
Number of US Weighted Cross Sections= 1
Number of DS Weighted Cross Sections= 1
Upstream XS Weight=0.25
Main XS Weight=0.5
Downstream XS Weight=0.25
Number of DS XS's Weighted with US Boundary= 1
Upstream Boundary Weight= 1
Weight of XSs Associated with US Boundary= 0
Number of US XS's Weighted with DS Boundary= 1
Downstream Boundary Weight= 0.5
Weight of XSs Associated with DS Boundary= 0.5
Sediment Output Level= 4
Mass or Volume Output= 0
Output Increment Type= 1
Profile and TS Output Increment= 10
XS Output Flag= 0
XS Output Increment= 10
Disregard all LS=0
Disregard all Conn=0
Disregard all Breaches=0
Disregard all Pumps=0

--- WMATA_JD.f02 (steady flow) ---

Flow Title=Clipped Flow
Program Version=4.10
Number of Profiles= 6
Profile Names=2-yr exist,10-yr exist,100-yr exist,2-yr ult,10-yr ult,100-yr ult
River Rch & RM=RIVER-1,Reach-1         ,521
    3138    7025   12941    3463    7219   13125
River Rch & RM=RIVER-1,Reach-1         ,519
    5097    9989   18755    5528   10227   19186
River Rch & RM=RIVER-1,Reach-1         ,518
    5164   10106   18931    5597   10345   19362
River Rch & RM=RIVER-1,Reach-1         ,509.8
    5629   10707   18515    6228   11403   18874
River Rch & RM=RIVER-1,Reach-1         ,500
    5629   10707   18515    6228   11403   18874
Boundary for River Rch & Prof#=RIVER-1,Reach-1         , 1
Up Type= 0
Dn Type= 1
Dn Known WS=17.83
Boundary for River Rch & Prof#=RIVER-1,Reach-1         , 2
Up Type= 0
Dn Type= 1
Dn Known WS=21.14
Boundary for River Rch & Prof#=RIVER-1,Reach-1         , 3
Up Type= 0
Dn Type= 1
Dn Known WS=27.12
Boundary for River Rch & Prof#=RIVER-1,Reach-1         , 4
Up Type= 0
Dn Type= 1
Dn Known WS=18.23
Boundary for River Rch & Prof#=RIVER-1,Reach-1         , 5
Up Type= 0
Dn Type= 1
Dn Known WS=20.98
Boundary for River Rch & Prof#=RIVER-1,Reach-1         , 6
Up Type= 0
Dn Type= 1
Dn Known WS=27.75
DSS Import GetInterval= 0
DSS Import GetPeak= 0
DSS Import FillOption= 0

--- WMATA_JD.g03 (geometry) ---

Geom Title=Full Buildout
Program Version=4.10

River Reach=RIVER-1         ,Reach-1
Reach XY= 2
             0.5            0.95             0.5            0.05

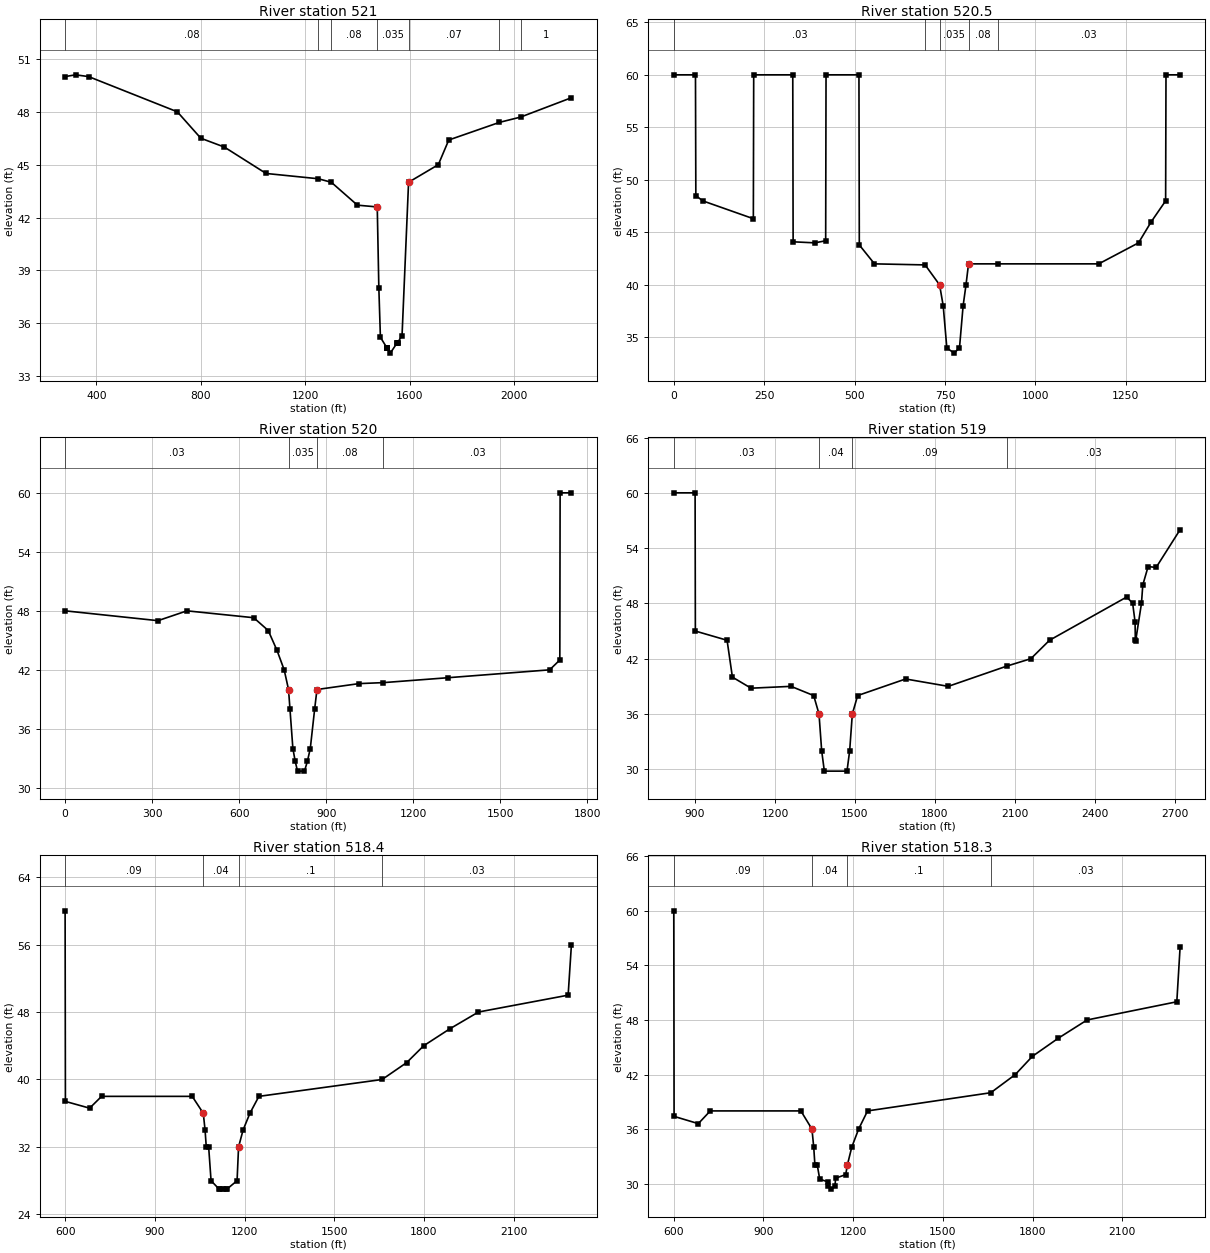
Type RM Length L Ch R = 1 ,521     ,290,370,450
#Sta/Elev= 29
     280      50     320    50.1     370      50     710      48     800    46.5
     890      46    1050    44.5    1250    44.2    1300      44    1400    42.7
    1476    42.6  1482.1      38  1488.1    35.2    1513    34.6  1513.1    34.6
  1514.2    34.6  1514.3    34.6    1526    34.3    1553    34.9  1553.1    34.9
  1554.2    34.9  1554.3    34.9    1571    35.3    1596      44    1710      45
    1750    46.4    1944    47.4    2025    47.7    2220    48.8
#Mann= 7 ,-1 , 0
     280     .08       0    1250     .03       0    1300     .08       0
    1476    .035       0    1596     .07       0    1944     .03       0
    2025       1       0
Bank Sta=1476,1596
XS Rating Curve= 0 ,0
Exp/Cntr=0.3,0.1

Type RM Length L Ch R = 1 ,520.5   ,670,620,530
#Sta/Elev= 30
       0      60      60      60      61    48.5      80      48     220    46.3
     221      60     329      60     330    44.1     390      44     420    44.2
     421      60     512      60     513    43.8     555      42     695    41.9
     735      40     745      38     755      34     775    33.5     790      34
     800      38     808      40     815      42     896      42    1175      42
    1285      44    1320      46    1360      48    1361      60    1400      60
#Mann= 5 ,-1 , 0
       0     .03       0     695     .08       0     735    .035       0
     815     .08       0     896     .03       0
#Block Obstruct= 2 , 0
             512      60     990            47.5
Bank Sta=735,815
XS Rating Curve= 0 ,0
Exp/Cntr=0.3,0.1

Type RM Length L Ch R = 1 ,520     ,1050,1170,1330
BEGIN DESCRIPTION:
DISCHARGES FROM ADDHYD 7 IN TR-20 RUN           ( D.A. = 35.35 MI^2 )
REPLACED WITH Q'S FROM ADDHYD 6 WHEN Q'S ARE HIGHER UPSTREAM.
END DESCRIPTION:
#Sta/Elev= 24
       0      48     320      47     420      48     650    47.3     700      46
     730      44     755      42     770      40     775      38     785      34
     793    32.7     801    31.7     825    31.7     835    32.7     845      34
     860      38     868      40    1013    40.6    1097    40.7    1320    41.2
    1670      42    1705      43    1706      60    1745      60
#Mann= 4 ,-1 , 0
       0     .03       0     770    .035       0     868     .08       0
    1097     .03       0
#Block Obstruct= 2 , 0
             600      60    1350            47.5
Bank Sta=770,868
XS Rating Curve= 0 ,0
Exp/Cntr=0.3,0.1

Type RM Length L Ch R = 1 ,519     ,330,320,265
BEGIN DESCRIPTION:
JUST DOWNSTREAM OF THE CONFLUENCE OF SLIGO CREEK
END DESCRIPTION:
#Sta/Elev= 30
     820      60     900      60     901      45    1020      44    1040      40
    1110    38.8    1260      39    1345      38    1365      36    1375      32
    1385    29.8    1470    29.8    1480      32    1490      36    1510      38
    1690    39.8    1850      39    2070    41.2    2160      42    2230      44
    2520    48.7    2542      48    2551      46    2552      44    2553    43.9
    2575      48    2580      50    2600      52    2630    51.9    2720      56
#Mann= 4 ,-1 , 0
     820     .03       0    1365     .04       0    1490     .09       0
    2070     .03       0
#Block Obstruct= 2 , 0
                            1900              44
Bank Sta=1365,1490
XS Rating Curve= 0 ,0
Exp/Cntr=0.3,0.1

Type RM Length L Ch R = 1 ,518.4   ,1,1,1
#Sta/Elev= 27
     600      60     601    37.4     682    36.6     722      38    1025      38
    1062      36    1068      34    1072      32    1080      32    1088      28
    1115      27    1117      27    1127      27    1139      27    1141      27
    1175      28    1180      32    1195      34    1218      36    1248      38
    1660      40    1742      42    1799      44    1886      46    1982      48
    2282      50    2293      56
#Mann= 4 ,-1 , 0
     600     .09       0    1062     .04       0    1180      .1       0
    1660     .03       0
#Block Obstruct= 2 , 0
                            1385              42
Bank Sta=1062,1180
XS Rating Curve= 0 ,0
Exp/Cntr=0.3,0.1

Type RM Length L Ch R = 1 ,518.3   ,4,4,4
BEGIN DESCRIPTION:
This is a REPEATED section.
DROP STRUCTURE
END DESCRIPTION:
#Sta/Elev= 27
     600      60     601    37.4     682    36.6     722      38    1025      38
    1062      36    1068      34    1072      32    1080      32    1088    30.5
    1115    30.2    1117    29.7    1127    29.4    1139    29.7    1141    30.6
    1175      31    1180      32    1195      34    1218      36    1248      38
    1660      40    1742      42    1799      44    1886      46    1982      48
    2282      50    2293      56
#Mann= 4 ,-1 , 0
     600     .09       0    1062     .04       0    1180      .1       0
    1660     .03       0
#Block Obstruct= 2 , 0
                            1384              42
Bank Sta=1062,1180
XS Rating Curve= 0 ,0
Exp/Cntr=0.3,0.1

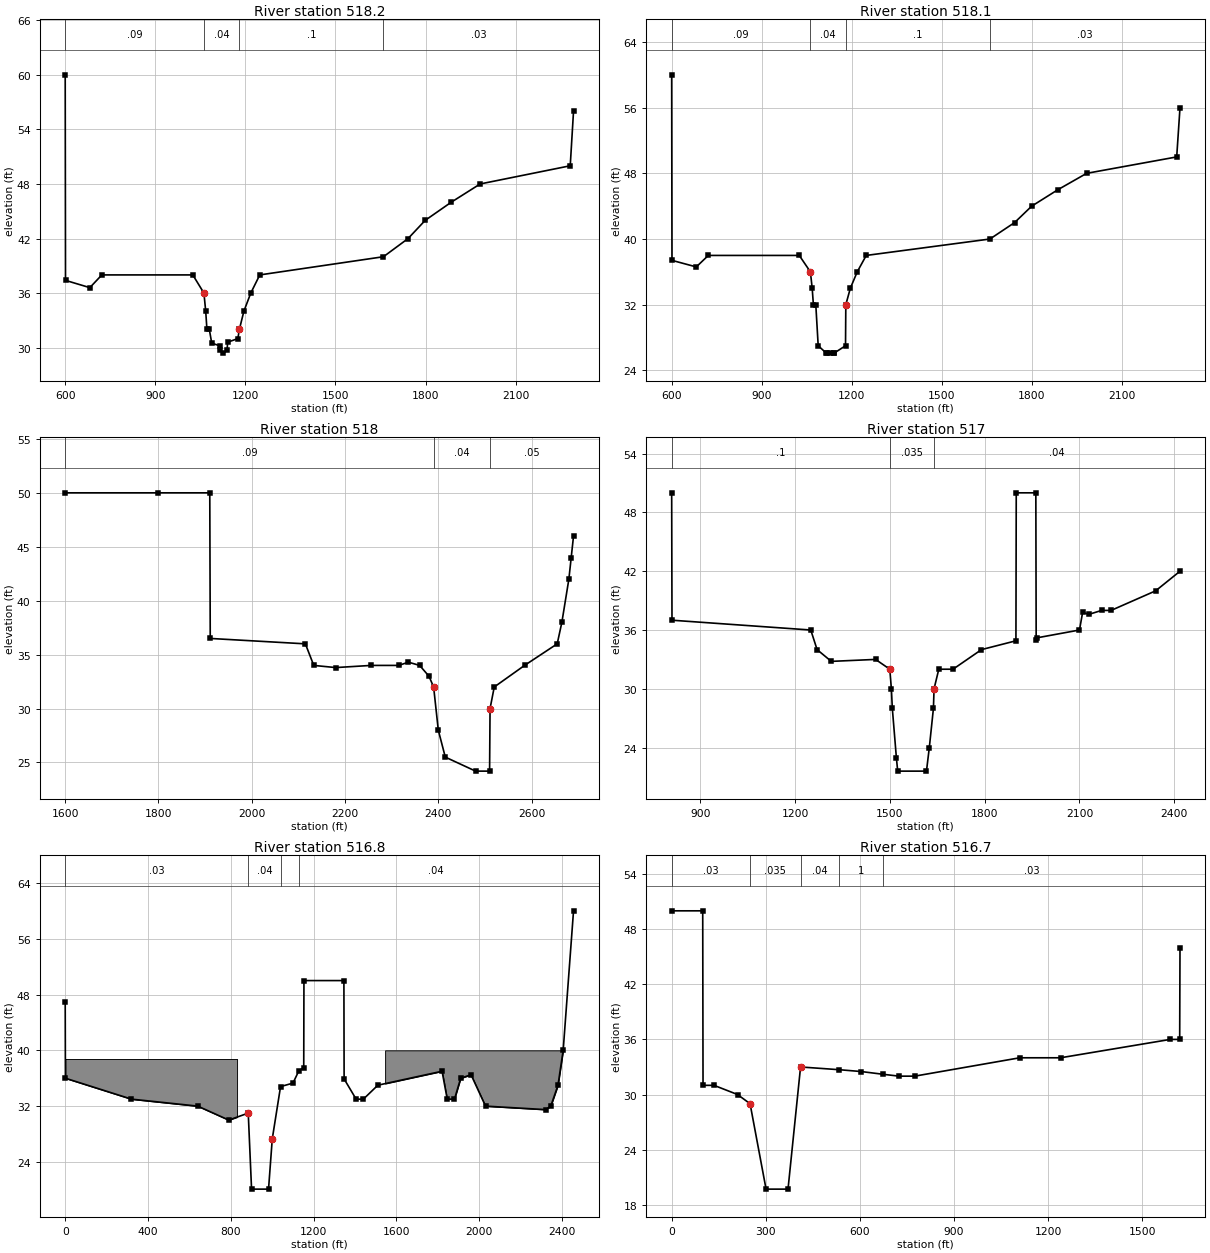
Type RM Length L Ch R = 1 ,518.2   ,20,20,20
#Sta/Elev= 27
     600      60     601    37.4     682    36.6     722      38    1025      38
    1062      36    1068      34    1072      32    1080      32    1088    30.5
    1115    30.2    1117    29.7    1127    29.4    1139    29.7    1141    30.6
    1175      31    1180      32    1195      34    1218      36    1248      38
    1660      40    1742      42    1799      44    1886      46    1982      48
    2282      50    2293      56
#Mann= 4 ,-1 , 0
     600     .09       0    1062     .04       0    1180      .1       0
    1660     .03       0
#Block Obstruct= 2 , 0
                            1380              42
Bank Sta=1062,1180
XS Rating Curve= 0 ,0
Exp/Cntr=0.3,0.1

Type RM Length L Ch R = 1 ,518.1   ,270,480,640
BEGIN DESCRIPTION:
DISCHARGES FROM ADDHYD 11 IN TR-20 RUN           ( D.A. = 46.58 MI^2 )
END DESCRIPTION:
#Sta/Elev= 27
     600      60     601    37.4     682    36.6     722      38    1025      38
    1062      36    1068      34    1072      32    1080      32    1088      27
    1115    26.1    1117    26.1    1127    26.1    1139    26.1    1141    26.1
    1179      27    1180      32    1195      34    1218      36    1248      38
    1660      40    1742      42    1799      44    1886      46    1982      48
    2282      50    2293      56
#Mann= 4 ,-1 , 0
     600     .09       0    1062     .04       0    1180      .1       0
    1660     .03       0
Bank Sta=1062,1180
XS Rating Curve= 0 ,0
Exp/Cntr=0.3,0.1

Type RM Length L Ch R = 1 ,518     ,770,800,870
BEGIN DESCRIPTION:
TOPOGRAPHIC SHEET S/2
JUST DOWNSTREAM OF CONFLUENCE OF NORTHWEST TRIB. 2
END DESCRIPTION:
#Sta/Elev= 25
    1600      50    1800      50    1910      50    1911    36.5    2115      36
    2133      34    2180    33.8    2256      34    2315      34    2336    34.3
    2360      34    2380      33    2390      32    2400      28    2415    25.5
    2480    24.2    2510    24.2    2511      30    2520      32    2585      34
    2655      36    2665      38    2680      42    2685      44    2690      46
#Mann= 3 , 0 , 0
    1600     .09       0    2390     .04       0    2511     .05       0
Bank Sta=2390,2511
XS Rating Curve= 0 ,0
Exp/Cntr=0.3,0.1

Type RM Length L Ch R = 1 ,517     ,365,385,400
#Sta/Elev= 30
     810      50     811      37    1250      36    1270      34    1315    32.8
    1455      33    1500      32    1505      30    1508      28    1521    22.9
    1525    21.6    1616    21.6    1625      24    1638      28    1640      30
    1655      32    1700      32    1790      34    1899    34.9    1900      50
    1962      50    1963      35    1965    35.2    2100      36    2110    37.8
    2130    37.6    2170      38    2200      38    2341      40    2418      42
#Mann= 3 , 0 , 0
     810      .1       0    1500    .035       0    1640     .04       0
#Block Obstruct= 2 , 0
                            2190              50
Bank Sta=1500,1640
XS Rating Curve= 0 ,0
Exp/Cntr=0.3,0.1

Type RM Length L Ch R = 1 ,516.8   ,180,180,180
BEGIN DESCRIPTION:
TOPOGRAPHIC SHEET T/1
END DESCRIPTION:
#Sta/Elev= 30
       0      47       1      36     320      33     640      32     790      30
     884      31     900    20.1     982    20.1    1000    27.3    1040    34.8
    1100    35.3    1129    37.1    1152    37.5    1153      50    1346      50
    1347    35.9    1405      33    1440      33    1510      35    1820      37
    1845      33    1880      33    1910      36    1960    36.5    2030      32
    2320    31.5    2345      32    2380      35    2405      40    2455      60
#Mann= 4 ,-1 , 0
       0     .03       0     884     .04       0    1040     .08       0
    1129     .04       0
#Block Obstruct= 2 ,-1
       0     830   38.76    1545    2500      40
Bank Sta=884,1000
XS Rating Curve= 0 ,0
Exp/Cntr=0.3,0.1

Type RM Length L Ch R = 1 ,516.7   ,1,1,1
#Sta/Elev= 19
       0      50      99      50     100      31     135      31     210      30
     250      29     301    19.7     371    19.7     411      33     535    32.7
     605    32.5     675    32.2     725      32     775      32    1110      34
    1240      34    1590      36    1620      36    1621      46
#Mann= 5 ,-1 , 0
       0     .03       0     250    .035       0     411     .04       0
     535       1       0     675     .03       0
#Block Obstruct= 2 , 0
                             925              40
Bank Sta=250,411
XS Rating Curve= 0 ,0
Exp/Cntr=0.3,0.1

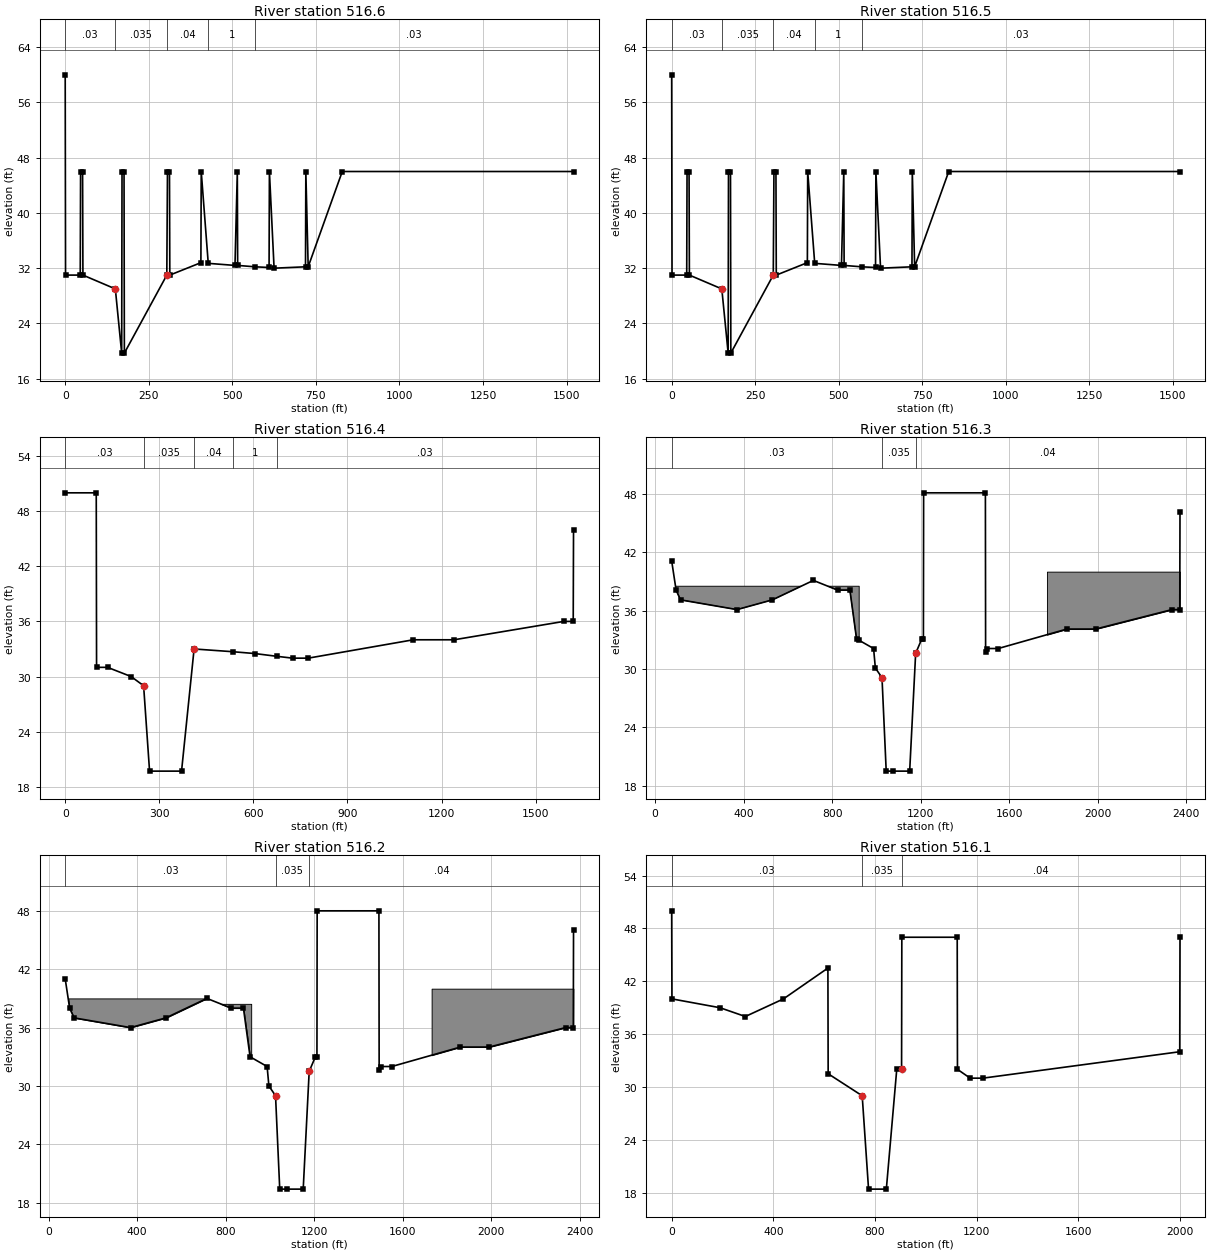
Type RM Length L Ch R = 1 ,516.6   ,40,40,40
BEGIN DESCRIPTION:
This is a REPEATED section.
END DESCRIPTION:
#Sta/Elev= 30
       0      60       1      31      45      31      46      46      52      46
      53      31     150      29     169    19.7     170      46     176      46
     177    19.7     304      31     306      46     312      46     313      31
     406    32.8     407      46     428    32.7     508    32.4     515      46
     516    32.4     568    32.2     610    32.1     611      46     625      32
     719    32.2     720      46     727    32.2     829      46    1521      46
#Mann= 5 ,-1 , 0
       0     .03       0     150    .035       0     304     .04       0
     428       1       0     568     .03       0
#Block Obstruct= 2 , 0
                             840              48
Bank Sta=150,304
XS Rating Curve= 0 ,0
Exp/Cntr=0.3,0.1

Type RM Length L Ch R = 1 ,516.5   ,1,1,1
BEGIN DESCRIPTION:
        METRO RAIL                   ( MINIMUM LOW CHORD ELEV. IS 46.6 )
END DESCRIPTION:
#Sta/Elev= 30
       0      60       1      31      45      31      46      46      52      46
      53      31     150      29     169    19.7     170      46     176      46
     177    19.7     304      31     306      46     312      46     313      31
     406    32.8     407      46     428    32.7     508    32.4     515      46
     516    32.4     568    32.2     610    32.1     611      46     625      32
     719    32.2     720      46     727    32.2     829      46    1521      46
#Mann= 5 ,-1 , 0
       0     .03       0     150    .035       0     304     .04       0
     428       1       0     568     .03       0
#Block Obstruct= 2 , 0
                             850              40
Bank Sta=150,304
XS Rating Curve= 0 ,0
Exp/Cntr=0.3,0.1

Type RM Length L Ch R = 1 ,516.4   ,130,130,130
#Sta/Elev= 19
       0      50      99      50     100      31     135      31     210      30
     250      29     269    19.7     371    19.7     411      33     535    32.7
     605    32.5     675    32.2     725      32     775      32    1110      34
    1240      34    1590      36    1620      36    1621      46
#Mann= 5 ,-1 , 0
       0     .03       0     250    .035       0     411     .04       0
     535       1       0     675     .03       0
#Block Obstruct= 2 , 0
                             945              40
Bank Sta=250,411
XS Rating Curve= 0 ,0
Exp/Cntr=0.3,0.1

Type RM Length L Ch R = 1 ,516.3   ,100,100,100
BEGIN DESCRIPTION:
This is a REPEATED section.
END DESCRIPTION:
#Sta/Elev= 29
      75    41.1      95    38.1     115    37.1     370    36.1     530    37.1
     715    39.1     825    38.1     880    38.1     910    33.1     922   32.94
     987    32.1     995    30.1    1025    29.1    1044    19.5    1075    19.5
    1150    19.5    1177    31.6    1205    33.1    1212    33.1    1213    48.1
    1492    48.1    1493    31.7    1500    32.1    1550    32.1    1860    34.1
    1990    34.1    2335    36.1    2370    36.1    2371    46.1
#Mann= 3 , 0 , 0
      75     .03       0    1025    .035       0    1177     .04       0
#Block Obstruct= 2 ,-1
      75     922    38.5    1770    2371      40
Bank Sta=1025,1177
XS Rating Curve= 0 ,0
Exp/Cntr=0.3,0.1

Type RM Length L Ch R = 1 ,516.2   ,250,250,250
#Sta/Elev= 28
      75      41      95      38     115      37     370      36     530      37
     715      39     825      38     880      38     910      33     987      32
     995      30    1025      29    1044    19.4    1075    19.4    1150    19.4
    1177    31.5    1205      33    1212      33    1213      48    1492      48
    1493    31.6    1500      32    1550      32    1860      34    1990      34
    2335      36    2370      36    2371      46
#Mann= 3 , 0 , 0
      75     .03       0    1025    .035       0    1177     .04       0
#Block Obstruct= 3 ,-1
       0     715      39     715     915   38.44    1730    2371      40
Bank Sta=1025,1177
XS Rating Curve= 0 ,0
Exp/Cntr=0.3,0.1

Type RM Length L Ch R = 1 ,516.1   ,480,500,515
BEGIN DESCRIPTION:
CROSS SECTIONS 516.1 TO 516.8 ARE FROM THE WEST HYATTSVILLE METRO
STATION FLOODPLAIN STUDY ( FPS 850140 ) ( FPS SECTIONS 1850 - 2850 )
END DESCRIPTION:
#Sta/Elev= 19
       0      50       1      40     190      39     290      38     440      40
     615    43.5     616    31.5     750      29     775    18.4     845    18.4
     886      32     905      32     906      47    1124      47    1125      32
    1175      31    1225      31    2000      34    2001      47
#Mann= 3 , 0 , 0
       0     .03       0     750    .035       0     905     .04       0
#XS Ineff= 2 , 0
             750      29     905              32
Permanent Ineff=
       F       F
#Block Obstruct= 2 , 0
             540      39    1405              47
Bank Sta=750,905
XS Rating Curve= 0 ,0
Exp/Cntr=0.3,0.1

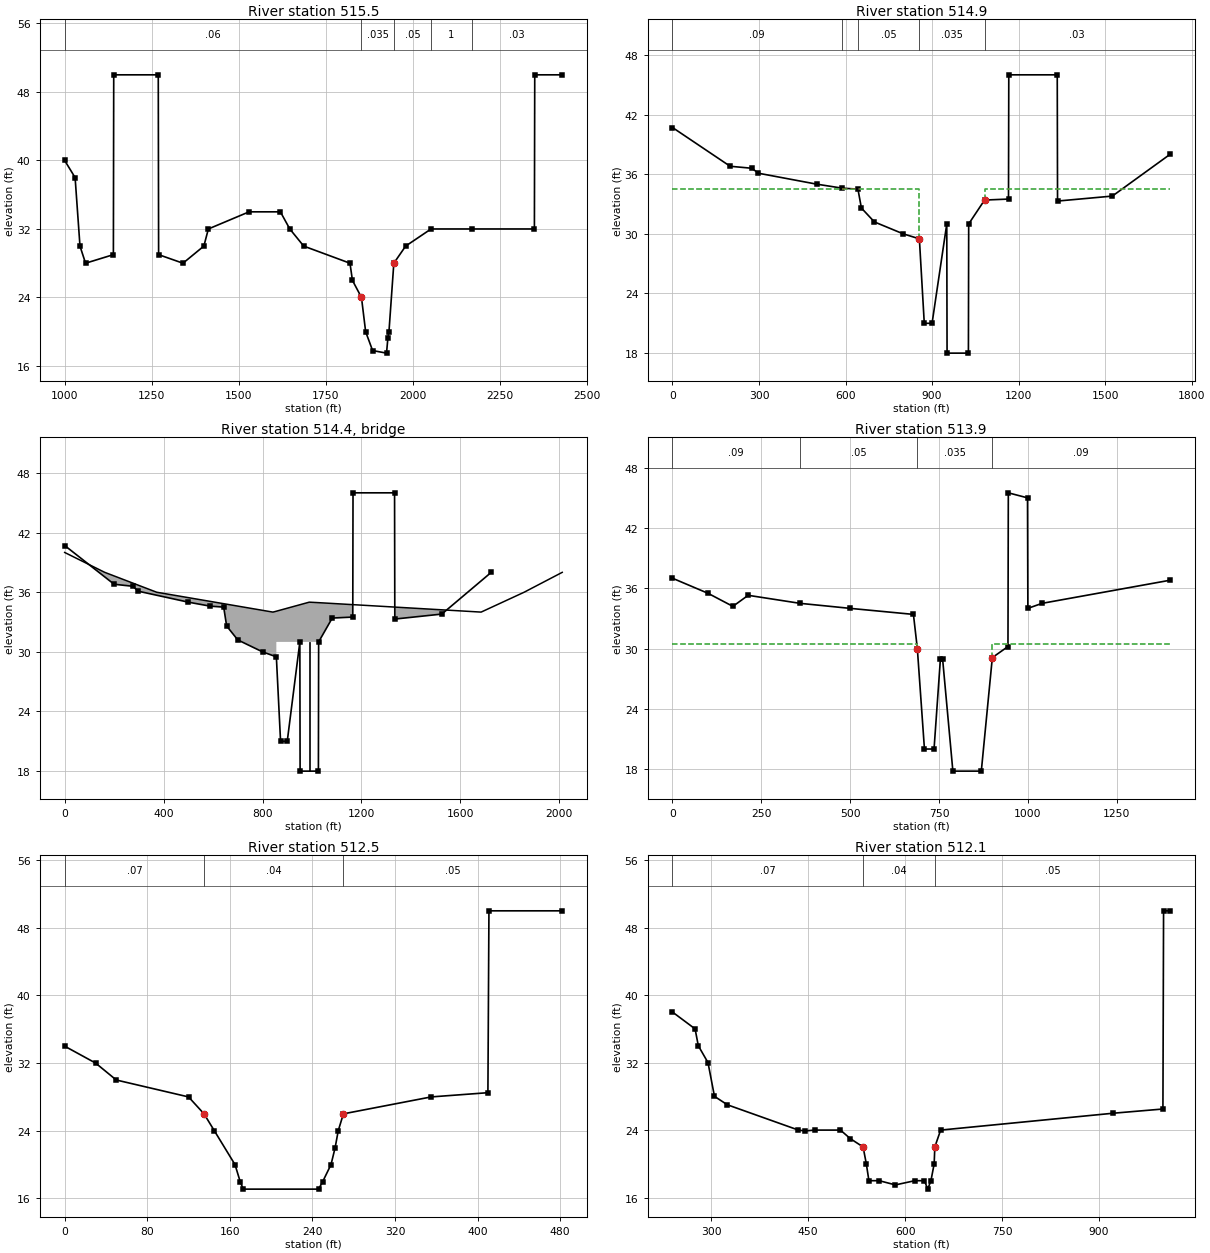
Type RM Length L Ch R = 1 ,515.5   ,160,145,90
#Sta/Elev= 30
    1000      40    1030      38    1044      30    1060      28    1140      29
    1141      50    1269      50    1270      29    1340      28    1400      30
    1413      32    1530      34    1620      34    1647      32    1687      30
    1820      28    1827      26    1853      24    1865      20    1885    17.8
    1925    17.5    1929    19.3    1932      20    1946      28    1980      30
    2053      32    2170      32    2350      32    2351      50    2430      50
#Mann= 5 ,-1 , 0
    1000     .06       0    1853    .035       0    1946     .05       0
    2053       1       0    2170     .03       0
#Block Obstruct= 2 , 0
            1495      39
Bank Sta=1853,1946
XS Rating Curve= 0 ,0
Exp/Cntr=0.5,0.3

Type RM Length L Ch R = 1 ,514.9   ,150,150,150
BEGIN DESCRIPTION:
QUEEN'S CHAPEL ROAD (MD 500)     (2 SPAN BRIDGE & 2- 132" BCCMP)
CROSS SECTION 1200 IN WEST HYATTSVILLE METRO STATION FLOODPLAIN STUDY
END DESCRIPTION:
#Sta/Elev= 24
       0    40.7     200    36.8     275    36.6     298    36.1     500      35
     588    34.6     643    34.5     655    32.6     700    31.2     800      30
     856    29.5     873      21     900      21     951      31     952      18
    1026      18    1027      31    1082    33.4    1165    33.5    1166      46
    1334      46    1335    33.3    1525    33.8    1725      38
#Mann= 5 ,-1 , 0
       0     .09       0     588     .03       0     643     .05       0
     856    .035       0    1082     .03       0
#XS Ineff= 2 , 0
             856    34.5    1082            34.5
Permanent Ineff=
       F       F
Bank Sta=856,1082
XS Rating Curve= 0 ,0
Exp/Cntr=0.5,0.3

Type RM Length L Ch R = 3 ,514.4   ,,,
BEGIN DESCRIPTION:
Queens Chapel Rd
END DESCRIPTION:
Bridge Culvert--1,0,-1,-1, 0
Deck Dist Width WeirC Skew NumUp NumDn MinLoCord MaxHiCord MaxSubmerge Is_Ogee
35,85,3,0, 12, 11, 34.5, , 0.98, 0, 0,0,,
       0     162     372     842     856     856     989    1027    1027    1684
    1858    2012
      40      38      36      34   34.09   34.09      35   34.95   34.95      34
      36      38
      15      15      15      15      15      31      31      31      15      15
                
       0     212     682     689     689     829     900     900    1288    1462
    1616
      38      36      34   34.03   34.03      35   34.85   34.85      34      36
      38
      15      15      15      15      31      31      31      15      15      15
      15
Pier Skew, UpSta & Num, DnSta & Num=  ,989, 2 ,829, 2 , 0 , 0 , 0 ,,
       5       5
      15      31
       5       5
      15      31
BR Coef= 0 , 0 , 1 ,1.1, 0 ,,,0.3,0,1.2,0,31
WSPro=,,,, 1 ,,,, 0 ,,,, 0 ,,,,-1 ,-1 ,-1 , 0 , 0 , 0 , 0 , 0
BC Design=,, 0 ,, 0 ,,,,,,
BC Use User HTab Curves=0
BC User HTab FreeFlow(D)= 0

Type RM Length L Ch R = 1 ,513.9   ,440,500,550
BEGIN DESCRIPTION:
CROSS SECTION 1100 IN WEST HYATTSVILLE METRO STATION FLOODPLAIN STUDY
END DESCRIPTION:
#Sta/Elev= 21
       0      37     100    35.5     170    34.2     213    35.3     359    34.5
     500      34     678    33.4     689      30     709      20     736      20
     754      29     760      29     789    17.8     869    17.8     900    29.1
     944    30.2     945    45.5     999      45    1000      34    1040    34.5
    1400    36.8
#Mann= 4 ,-1 , 0
       0     .09       0     359     .05       0     689    .035       0
     900     .09       0
#XS Ineff= 2 , 0
             689    30.5     900            30.5
Permanent Ineff=
       F       F
Bank Sta=689,900
XS Rating Curve= 0 ,0
Exp/Cntr=0.5,0.3

Type RM Length L Ch R = 1 ,512.5   ,410,415,470
BEGIN DESCRIPTION:
LEVEE IN RIGHT OVERBANK
END DESCRIPTION:
#Sta/Elev= 19
       0      34      30      32      50      30     120      28     135      26
     145      24     165      20     170      18     173    17.1     246    17.1
     250      18     258      20     262      22     265      24     270      26
     355      28     410    28.5     411      50     482      50
#Mann= 3 , 0 , 0
       0     .07       0     135     .04       0     270     .05       0
Bank Sta=135,270
XS Rating Curve= 0 ,0
Exp/Cntr=0.3,0.1

Type RM Length L Ch R = 1 ,512.1   ,1,1,1
BEGIN DESCRIPTION:
LEVEE IN RIGHT OVERBANK
END DESCRIPTION:
#Sta/Elev= 27
     240      38     275      36     280      34     295      32     305      28
     325      27     435      24     445    23.9     460      24     500      24
     515      23     535      22     540      20     544      18     560      18
     585    17.5     615      18     630      18     635      17     640      18
     645      20     646      22     655      24     922      26     999    26.5
    1000      50    1010      50
#Mann= 3 , 0 , 0
     240     .07       0     535     .04       0     646     .05       0
Bank Sta=535,646
XS Rating Curve= 0 ,0
Exp/Cntr=0.3,0.1

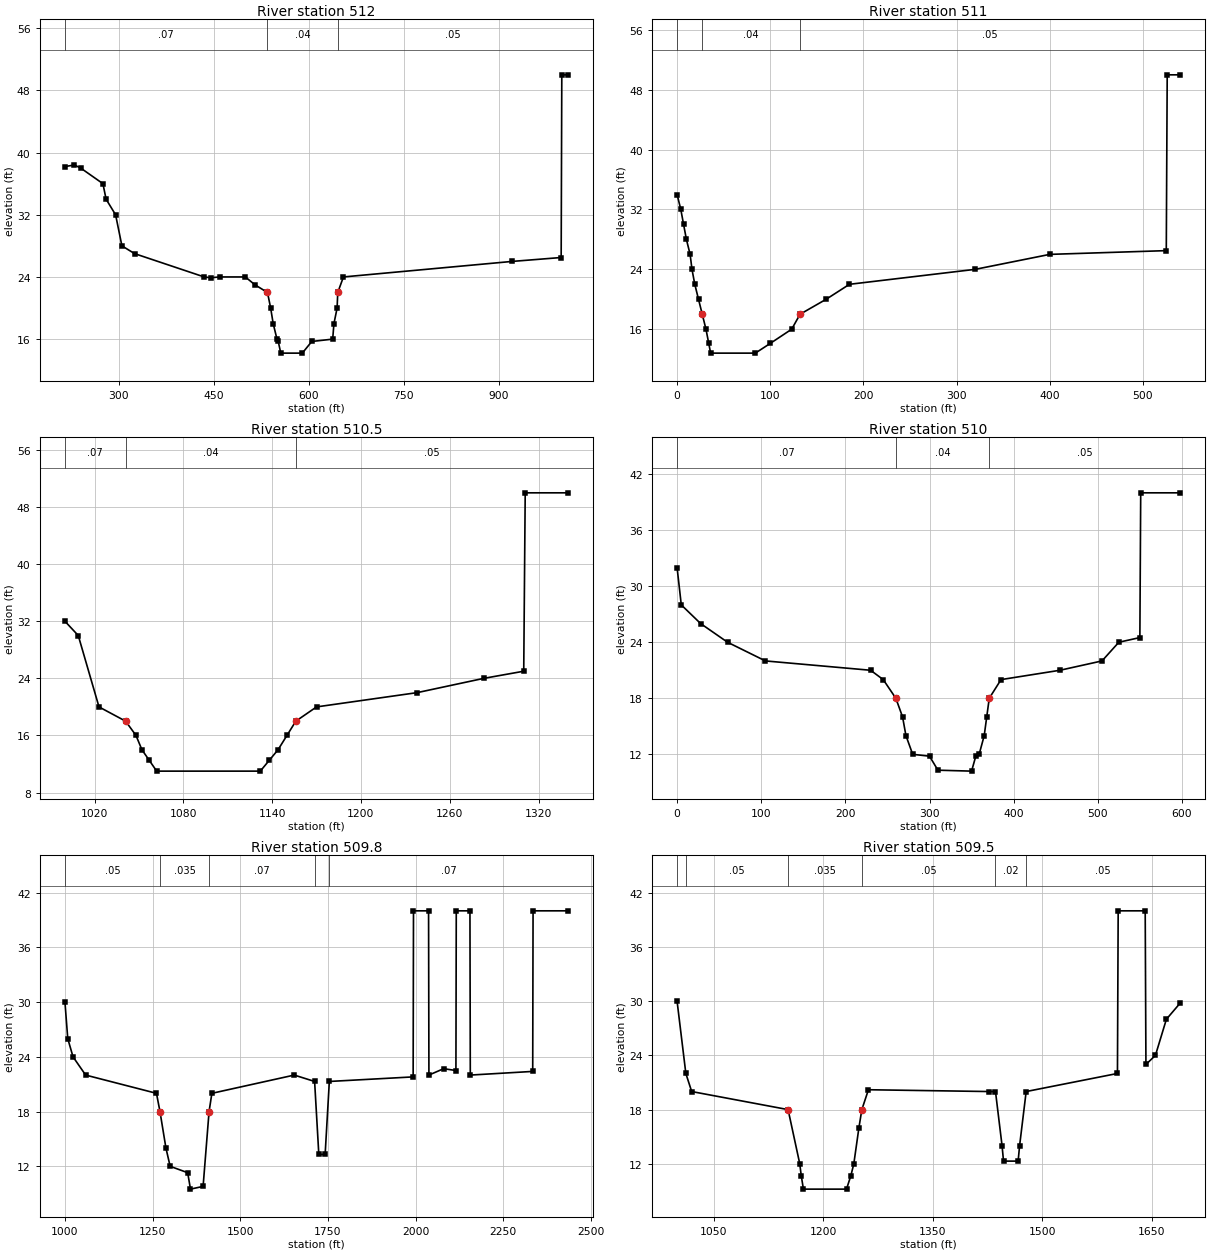
Type RM Length L Ch R = 1 ,512     ,1300,1030,550
BEGIN DESCRIPTION:
LEVEE IN RIGHT OVERBANK
END DESCRIPTION:
#Sta/Elev= 30
     215    38.2     230    38.4     240      38     275      36     280      34
     295      32     305      28     325      27     435      24     445    23.9
     460      24     500      24     515      23     535      22     540      20
     544      18     550      16     552    15.7     556    14.2     590    14.2
     605    15.7     638      16     640      18     645      20     646      22
     655      24     922      26     999    26.5    1000      50    1010      50
#Mann= 3 , 0 , 0
     215     .07       0     535     .04       0     646     .05       0
Bank Sta=535,646
XS Rating Curve= 0 ,0
Exp/Cntr=0.3,0.1

Type RM Length L Ch R = 1 ,511     ,625,625,630
BEGIN DESCRIPTION:
LEVEE IN RIGHT OVERBANK
END DESCRIPTION:
#Sta/Elev= 23
       0      34       4      32       7      30      10      28      14      26
      16      24      19      22      23      20      27      18      31      16
      34    14.1      36    12.8      84    12.8     100    14.1     123      16
     132      18     160      20     185      22     320      24     400      26
     525    26.5     526      50     540      50
#Mann= 3 , 0 , 0
       0     .07       0      27     .04       0     132     .05       0
Bank Sta=27,132
XS Rating Curve= 0 ,0
Exp/Cntr=0.3,0.1

Type RM Length L Ch R = 1 ,510.5   ,290,300,320
BEGIN DESCRIPTION:
LEVEE IN RIGHT OVERBANK
END DESCRIPTION:
#Sta/Elev= 19
    1000      32    1009      30    1023      20    1041      18    1048      16
    1052      14    1057    12.5    1062      11    1132      11    1138    12.5
    1144      14    1150      16    1156      18    1170      20    1238      22
    1283      24    1310      25    1311      50    1340      50
#Mann= 3 , 0 , 0
    1000     .07       0    1041     .04       0    1156     .05       0
Bank Sta=1041,1156
XS Rating Curve= 0 ,0
Exp/Cntr=0.3,0.1

Type RM Length L Ch R = 1 ,510     ,180,300,370
BEGIN DESCRIPTION:
DISCHARGES FROM ADDHYD 15 IN TR-20 RUN          ( D.A. = 49.69 MI^2 )
REPLACED WITH Q'S FROM ADDHYD 113 WHEN Q'S ARE HIGHER UPSTREAM.
LEVEE IN RIGHT OVERBANK
END DESCRIPTION:
#Sta/Elev= 26
       0      32       5      28      28      26      60      24     105      22
     230      21     245      20     260      18     268      16     272      14
     280      12     300    11.8     310    10.3     350    10.2     355    11.8
     359      12     365      14     368      16     371      18     385      20
     455      21     505      22     525      24     550    24.5     551      40
     598      40
#Mann= 3 , 0 , 0
       0     .07       0     260     .04       0     371     .05       0
Bank Sta=260,371
XS Rating Curve= 0 ,0
Exp/Cntr=0.3,0.1

Type RM Length L Ch R = 1 ,509.8   ,450,400,335
#Sta/Elev= 30
    1000      30    1008      26    1023      24    1059      22    1261      20
    1271      18    1288      14    1300      12    1350    11.3    1358     9.5
    1394     9.8    1411      18    1419      20    1654      22    1712    21.3
    1724    13.3    1742    13.3    1754    21.3    1993    21.8    1994      40
    2037      40    2038      22    2080    22.7    2115    22.5    2116      40
    2155      40    2156      22    2334    22.4    2335      40    2435      40
#Mann= 5 ,-1 , 0
    1000     .05       0    1271    .035       0    1411     .07       0
    1712     .02       0    1754     .07       0
Bank Sta=1271,1411
XS Rating Curve= 0 ,0
Exp/Cntr=0.3,0.1

Type RM Length L Ch R = 1 ,509.5   ,45,45,45
#Sta/Elev= 27
    1000      30    1012      22    1020      20    1152      18    1168      12
    1170    10.7    1173     9.2    1232     9.2    1238    10.7    1242      12
    1249      16    1253      18    1262    20.2    1427      20    1436      20
    1445      14    1447    12.3    1467    12.3    1469      14    1478      20
    1603      22    1604      40    1641      40    1642      23    1655      24
    1670      28    1689    29.8
#Mann= 6 ,-1 , 0
    1000      .1       0    1012     .05       0    1152    .035       0
    1253     .05       0    1436     .02       0    1478     .05       0
Bank Sta=1152,1253
XS Rating Curve= 0 ,0
Exp/Cntr=0.5,0.3