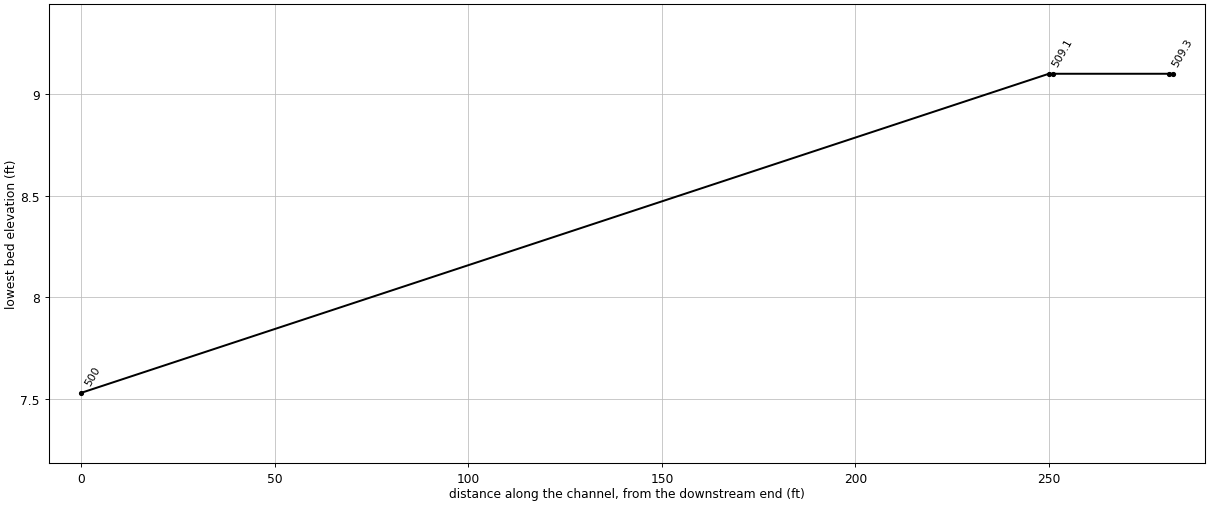
HEC-RAS study WMATA_JD.prj: WMATA_JD

--- WMATA_JD.g03 (geometry) --- (continued)

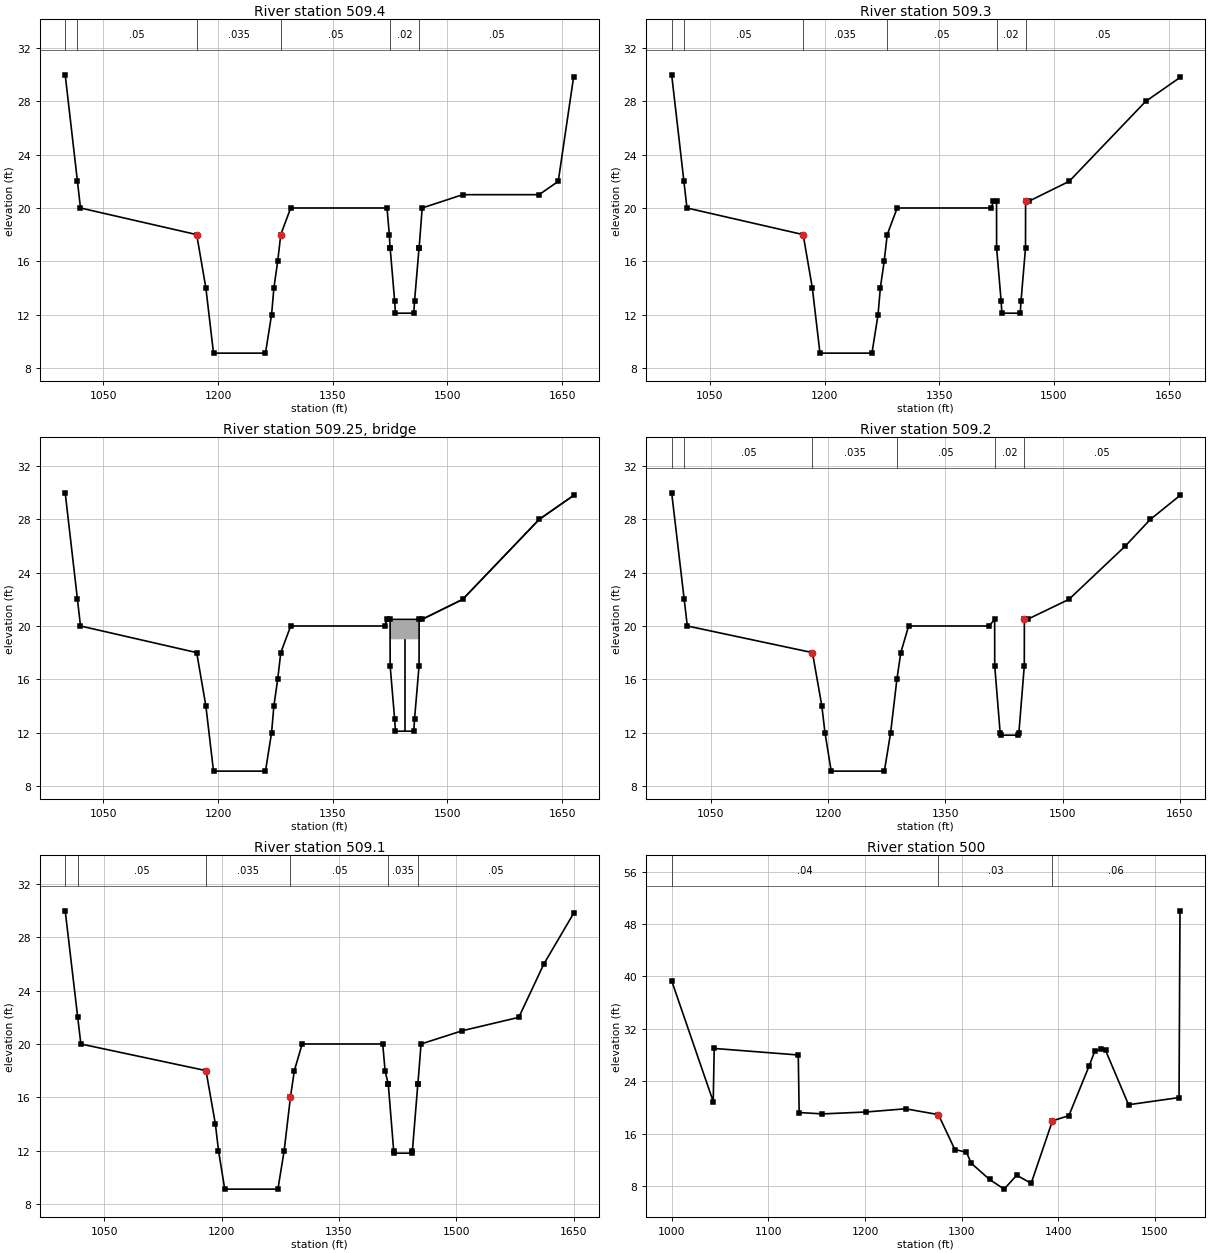
Type RM Length L Ch R = 1 ,509.4   ,1,1,1
#Sta/Elev= 27
    1000      30    1016      22    1020      20    1172      18    1184      14
    1194     9.1    1262     9.1    1270      12    1273      14    1278      16
    1282      18    1295      20    1421      20    1424      18    1425      17
  1425.1      17    1431      13    1432    12.1    1456    12.1    1457      13
  1462.9      17    1463      17    1467      20    1520      21    1620      21
    1645      22    1665    29.8
#Mann= 6 ,-1 , 0
    1000      .1       0    1016     .05       0    1172    .035       0
    1282     .05       0    1425     .02       0    1463     .05       0
Bank Sta=1172,1282
XS Rating Curve= 0 ,0
Exp/Cntr=0.5,0.3

Type RM Length L Ch R = 1 ,509.3   ,20,30,30
BEGIN DESCRIPTION:
        PRIVATE DRIVE OVER NORTHWEST TRIBUTARY #1
END DESCRIPTION:
#Sta/Elev= 26
    1000      30    1016      22    1020      20    1172      18    1184      14
    1194     9.1    1262     9.1    1270      12    1273      14    1278      16
    1282      18    1295      20    1418      20    1421    20.5    1425    20.5
  1425.1      17    1431      13    1432    12.1    1456    12.1    1457      13
  1462.9      17    1463    20.5    1467    20.5    1520      22    1620      28
    1665    29.8
#Mann= 6 ,-1 , 0
    1000      .1       0    1016     .05       0    1172    .035       0
    1282     .05       0    1425     .02       0    1463     .05       0
Bank Sta=1172,1463
XS Rating Curve= 0 ,0
Exp/Cntr=0.5,0.3

Type RM Length L Ch R = 3 ,509.25  ,,,
BEGIN DESCRIPTION:
Bridge #1, private drive
END DESCRIPTION:
Bridge Culvert--1,0,-1,-1, 0
Deck Dist Width WeirC Skew NumUp NumDn MinLoCord MaxHiCord MaxSubmerge Is_Ogee
4,25,2.6,0, 18, 17, , , 0.98, 0, 0,0,,
    1418    1421    1424    1425  1425.1    1431    1432  1443.5  1444.6    1456
    1457  1462.9    1463    1467    1520    1620    1645    1665
      20    20.5    20.5    20.5    20.5    20.5    20.5    20.5    20.5    20.5
    20.5    20.5    20.5    20.5      22      28      29    29.8
      20    20.5    20.5    20.5      19      19      19      19      19      19
      19      19    20.5    20.5      22      28      29    29.8
    1406    1409    1413  1413.1    1420    1421  1431.5  1432.6    1443    1444
  1450.9    1451    1455    1508    1580    1612    1650
      20    20.2    20.5    20.5    20.5    20.5    20.5    20.5    20.5    20.5
    20.5    20.5    20.5      22      26      28    29.8
      20    20.2    20.5      19      19      19      19      19      19      19
      19    20.5    20.5      22      26      28    29.8
Pier Skew, UpSta & Num, DnSta & Num=  ,1444, 2 ,1432, 2 , 0 , 0 , 0 ,,
       1       1
      10      20
       1       1
      10      20
BR Coef=-1 , 0 , 0 ,, 0 ,,,0.8,-1,,1,
WSPro=,,,, 1 ,,,, 0 ,,,, 0 ,,,,-1 ,-1 ,-1 , 0 , 0 , 0 , 0 , 0
BC Design=,, 0 ,, 0 ,,,,,,
BC Use User HTab Curves=0
BC User HTab FreeFlow(D)= 0

Type RM Length L Ch R = 1 ,509.2   ,1,1,1
#Sta/Elev= 26
    1000      30    1016      22    1020      20    1180      18    1192      14
    1196      12    1204     9.1    1272     9.1    1280      12    1288      16
    1293      18    1303      20    1406      20    1413    20.5  1413.1      17
    1420      12    1421    11.8    1443    11.8    1444      12  1450.9      17
    1451    20.5    1455    20.5    1508      22    1580      26    1612      28
    1650    29.8
#Mann= 6 ,-1 , 0
    1000      .1       0    1016     .05       0    1180    .035       0
    1288     .05       0    1413     .02       0    1451     .05       0
Bank Sta=1180,1451
XS Rating Curve= 0 ,0
Exp/Cntr=0.5,0.3

Type RM Length L Ch R = 1 ,509.1   ,140,250,270
BEGIN DESCRIPTION:
DISCHARGES FROM ADDHYD 17 IN TR-20 RUN          ( D.A. = 51.66 MI^2 )
END DESCRIPTION:
#Sta/Elev= 27
    1000      30    1016      22    1020      20    1180      18    1192      14
    1196      12    1204     9.1    1272     9.1    1280      12    1288      16
    1293      18    1303      20    1406      20    1409      18    1413      17
  1413.1      17    1420      12    1421    11.8    1443    11.8    1444      12
  1450.9      17    1451      17    1455      20    1508      21    1580      22
    1612      26    1650    29.8
#Mann= 6 ,-1 , 0
    1000      .1       0    1016     .05       0    1180    .035       0
    1288     .05       0    1413    .035       0    1451     .05       0
Bank Sta=1180,1288
XS Rating Curve= 0 ,0
Exp/Cntr=0.5,0.3

Type RM Length L Ch R = 1 ,500     ,368,368,368
BEGIN DESCRIPTION:
        ****************************************************************
        *** CROSS SECTIONS ORIENTED LEFT TO RIGHT LOOKING DOWNSTREAM ***
        ****************************************************************
        STARTING WATER SURFACE ELEVATION FROM DOWNSTREAM HEC2 RUN
DISCHARGES FROM ADDHYD 99 IN TR-20 RUN ( D.A. = 52.79 MI^2 )
REPLACED WITH DISCHARGES FROM ADDHYD 17 WHEN HIGHER
END DESCRIPTION:
#Sta/Elev= 25
    1000   39.32    1043   20.89    1044      29    1131      28 1131.92   19.22
    1156   19.01    1201    19.3    1242   19.79    1276    18.9    1293   13.57
    1305   13.16    1310   11.48    1329       9    1344    7.53    1357    9.65
    1372    8.42    1394   17.95    1411   18.74    1432   26.34    1438   28.65
    1444   28.88    1449   28.69 1472.77   20.41    1525    21.5    1526      50
#Mann= 3 , 0 , 0
    1000     .04       0    1276     .03       0    1394     .06       0
#Block Obstruct= 2 , 0
                            1444
Bank Sta=1276,1394
XS Rating Curve= 0 ,0
Exp/Cntr=0.3,0.1

Chan Stop Cuts=-1
Use User Specified Reach Order=0
Composite Channel Slope=5